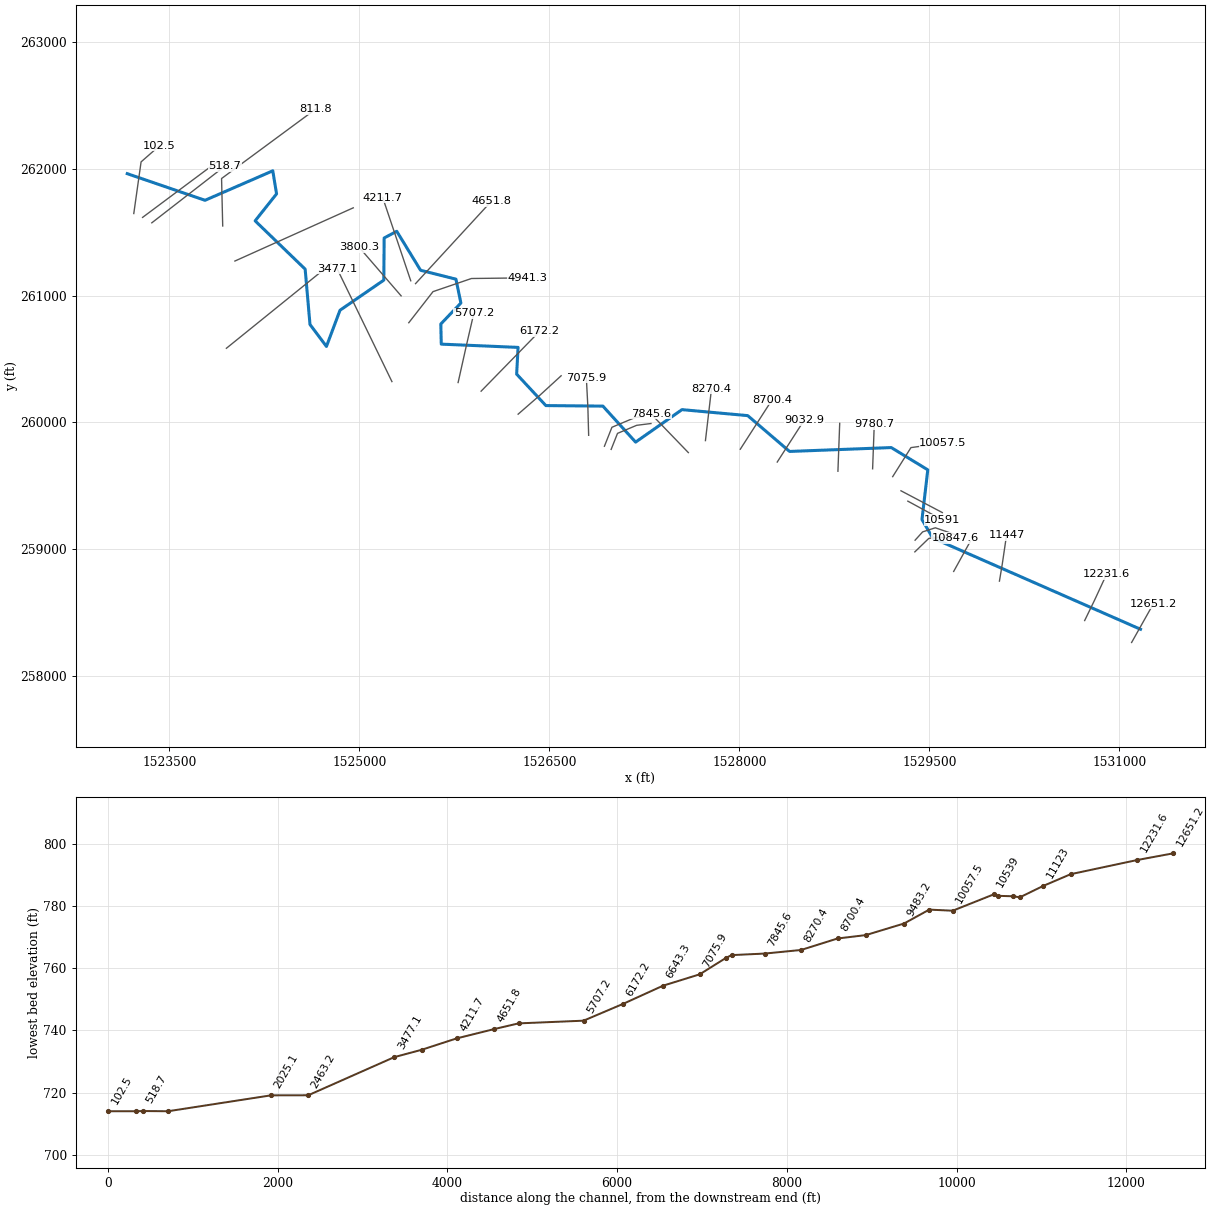
--- BACKRN.prj (project) ---

Proj Title=BACKRN
Current Plan=p01
Default Exp/Contr=0,0
English Units
Geom File=g01
Flow File=f01
Plan File=p01
BEGIN DESCRIPTION:
END DESCRIPTION:
DSS Export Rating Curves= 0
DSS Export Rating Curve Sorted= 0
DSS Export Volume Flow Curves= 0
DXF OffsetX= 0
DXF OffsetY= 0
DXF ScaleX= 0
DXF ScaleY= 0

--- BACKRN.p01 (plan) ---

Plan Title=Floodplain
Program Version=4.00
Geom File=g01
Flow File=f01
K Sum by GR=0
Std Step Tol=0.01
Critical Tol=0.01
Num of Std Step Trials=20
Max Error Tol=0.3
Flow Tol Ratio=0.001
Split Flow NTrial=30
Split Flow Tol=0.02
Split Flow Ratio=0.02
Log Output Level=0
Friction Slope Method=1
Unsteady Friction Slope Method=2
Unsteady Bridges Friction Slope Method=1
Global Log Level=0
CheckData=False
Run HTab=0
Run UNet=0
Run PostProcess=0
UNET Theta=0
UNET Theta Warmup=0
UNET ZTol=0
UNET ZSATol=0
UNET MxIter=0
UNET MaxInSteps=0
UNET DtIC=0
UNET DtMin=0
UNET MaxCRTS=0
UNET WFStab=0
UNET SFStab=0
UNET WFX=0
UNET SFX=0
UNET DSS MLevel=0
UNET DZMax Abort=0
UNET Convert EG Bridges=0
UNET Use Existing IB Tables=0
UNET Froude Limit=0
UNET Froude Power=0
Write IC File=0
Echo Input=False
Echo Output=False
Write Detailed=0

--- BACKRN.f01 (steady flow) ---

Flow Title=NFF Regression Equation
Program Version=4.00
Number of Profiles=1
Profile Names=P100yr
River Rch & RM=BACKRN,Main      ,12651.2
855.6779
River Rch & RM=BACKRN,Main      ,12231.6
893.1089
River Rch & RM=BACKRN,Main      ,8270.4
990.1094
River Rch & RM=BACKRN,Main      ,4941.3
1099.683
River Rch & RM=BACKRN,Main      ,4651.8
1387.695
River Rch & RM=BACKRN,Main      ,518.7
1447.240
River Rch & RM=BACKRN,Main      ,102.5
1448.776
Boundary for River Rch & Prof#=BACKRN,Main      ,1
Up Type=0
Dn Type=3
Dn Slope=0.000351

--- BACKRN.g01 (geometry) ---

Geom Title=USGS 10m DEM
Program Version=4.10

River Reach=BACKRN          ,Main
Reach XY= 30
     1531166.032      258368.058     1529526.661       259087.45
     1529441.244      259233.283     1529487.078      259625.644
     1529198.883      259801.339     1528396.106      259770.783
      1528065.55      260053.422       1527546.8      260100.644
     1527180.828      259844.394     1526922.495      260128.422
     1526472.494      260132.589     1526241.939      260380.505
      1526253.05      260591.617       1525646.8      260617.311
     1525643.328      260776.339     1525801.661      260941.617
     1525762.772      261129.811     1525483.606       261199.95
     1525295.411      261507.589     1525196.106      261454.811
     1525193.328      261122.172     1524847.494      260884.672
      1524740.55      260599.256     1524610.689      260772.172
     1524572.495      261208.978     1524177.603      261589.915
       1524346.8      261802.728     1524316.939      261984.672
     1523782.217      261752.033     1523168.107      261962.151

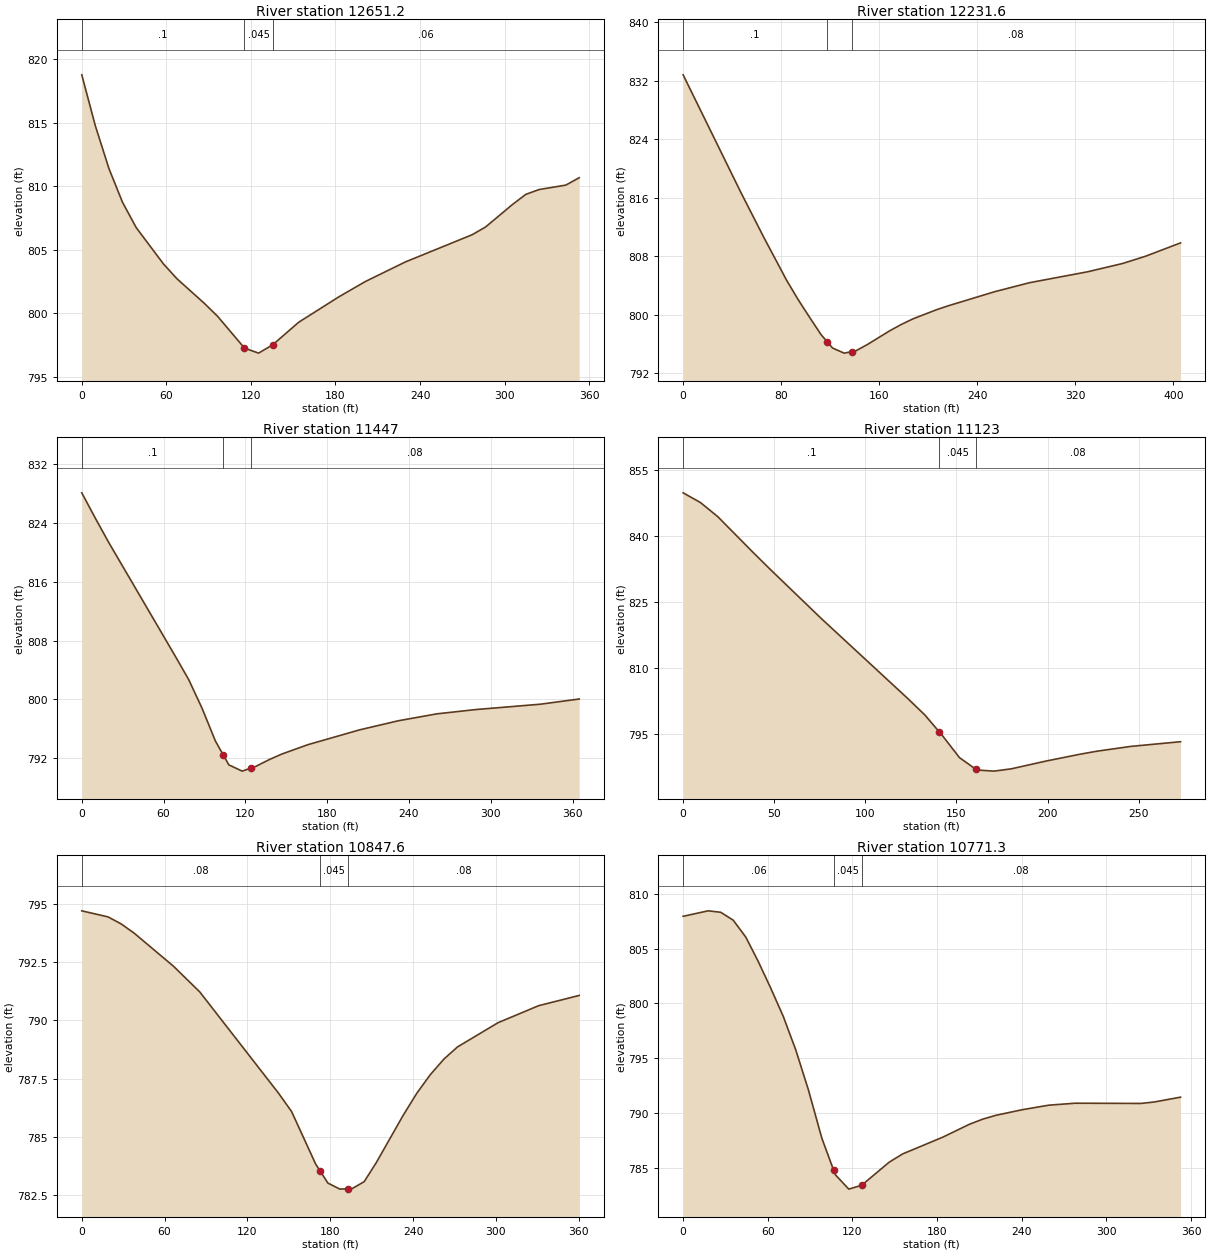
Type RM Length L Ch R = 1 ,12651.2 ,418.2,419.6,420.9
XS GIS Cut Line= 3
     1531095.846      258263.679     1531157.316       258372.96
     1531268.849      258571.244
#Sta/Elev= 23
       0  818.76     9.6  814.76    19.3  811.38    28.9  808.74    38.6  806.75
    57.9   803.9    67.5  802.73    86.8  800.81    96.4  799.77   115.4797.2797
   125.4  796.88   135.4797.5289   153.8   799.3   182.3   801.3   201.2  802.51
   229.6  804.05     277  806.19   286.5   806.8   305.5  808.56     315  809.36
   324.4  809.74   343.4  810.09   352.9  810.67
#Mann= 3 , 0 , 0
       0      .1       0   115.4    .045       0   135.4     .06       0
Bank Sta=115.4,135.4
XS Rating Curve= 0 ,0
Exp/Cntr=0.3,0.1

Type RM Length L Ch R = 1 ,12231.6 ,777.7,784.6,790.9
XS GIS Cut Line= 3
     1530725.364      258436.791     1530803.308      258597.176
     1530898.965       258803.64
#Sta/Elev= 24
       0  832.78    46.9  816.79    65.7  810.62    84.5   804.7    93.8  802.09
   103.2  799.65   112.6  797.28   117.4796.3463     122  795.45   131.4  794.76
   137.4794.9505   140.8  795.06   150.2  795.92   168.9  797.84   178.3   798.7
   187.8  799.46   206.8  800.69   216.2  801.22   254.2  803.15   282.6  804.38
     330  805.87   358.5     807   377.4     808   405.9  809.82
#Mann= 3 , 0 , 0
       0      .1       0   117.4    .045       0   137.4     .08       0
Bank Sta=117.4,137.4
XS Rating Curve= 0 ,0
Exp/Cntr=0.3,0.1

Type RM Length L Ch R = 1 ,11447   ,331.7,324,316.4
XS GIS Cut Line= 3
      1530052.62      258747.875     1530075.194      258883.339
      1530108.44      259108.445
#Sta/Elev= 21
       0  828.13     9.8  824.72    19.6  821.42    68.7  805.83    78.5  802.65
    88.3  798.74    98.1  794.27   103.9792.3623   107.9  791.05   117.7   790.2
   123.9790.5999   127.5  790.83   137.3  791.75   146.8  792.53   165.8   793.8
   203.7  795.82   232.1  797.06   260.6  798.01     289  798.59   336.4  799.32
   364.9  800.03
#Mann= 3 , 0 , 0
       0      .1       0   103.9    .045       0   123.9     .08       0
Bank Sta=103.9,123.9
XS Rating Curve= 0 ,0
Exp/Cntr=0.3,0.1

Type RM Length L Ch R = 1 ,11123   ,297.9,275.4,241.3
XS GIS Cut Line= 3
     1529691.442      258824.232     1529801.519      259023.328
      1529823.55      259063.175
#Sta/Elev= 20
       0   849.9     9.5  847.69      19  844.47    37.9  836.52    47.4  832.61
    75.8  821.24   123.2  803.02   132.7  799.22   140.7795.3126   142.2  794.58
   151.7  789.49   160.7786.8283   161.2  786.68   170.6  786.42   180.1  786.94
   199.1  788.71     218  790.29   227.5  790.99   245.7  792.06     273  793.13
#Mann= 3 , 0 , 0
       0      .1       0   140.7    .045       0   160.7     .08       0
Bank Sta=140.7,160.7
XS Rating Curve= 0 ,0
Exp/Cntr=0.3,0.1

Type RM Length L Ch R = 1 ,10847.6 ,70.6,76.3,92.9
XS GIS Cut Line= 4
     1529384.996      258978.545     1529494.303      259084.216
     1529554.758      259094.199     1529701.756      259088.418
#Sta/Elev= 24
       0   794.7      19  794.44    28.5  794.14      38  793.74    66.5  792.32
    85.5  791.22   142.5  786.88     152  786.09   169.5  783.83   172.7783.5381
   178.3  783.02     187  782.76   192.7782.7745   195.8  782.78   204.6  783.08
   213.3  783.89   232.9  785.93   242.7  786.87   252.5  787.67   262.4  788.34
   272.2  788.86   301.6   789.9     331  790.63   360.4  791.07
#Mann= 3 , 0 , 0
       0     .08       0   172.7    .045       0   192.7     .08       0
Bank Sta=172.7,192.7
XS Rating Curve= 0 ,0
Exp/Cntr=0.3,0.1

Type RM Length L Ch R = 1 ,10771.3 ,198.6,180.3,161.9
XS GIS Cut Line= 4
     1529386.855      259070.708     1529446.575      259136.316
       1529546.5      259168.523     1529696.801      259117.322
#Sta/Elev= 27
       0  807.93    17.7  808.43    26.6   808.3    35.5  807.58    44.4  806.04
    53.2  803.83    62.1  801.39      71  798.81    79.8  795.78    88.7  792.17
    98.3  787.74   106.6784.8394   107.8  784.42   117.4   783.1   126.6783.4582
     146  785.55   155.5   786.3   184.2  787.84     203  789.01   212.4  789.47
   221.7  789.82   240.4  790.33   259.1  790.74   277.8  790.92   324.5   790.9
   333.8  791.03   352.5  791.47
#Mann= 3 , 0 , 0
       0     .06       0   106.6    .045       0   126.6     .08       0
Bank Sta=106.6,126.6
XS Rating Curve= 0 ,0
Exp/Cntr=0.3,0.1

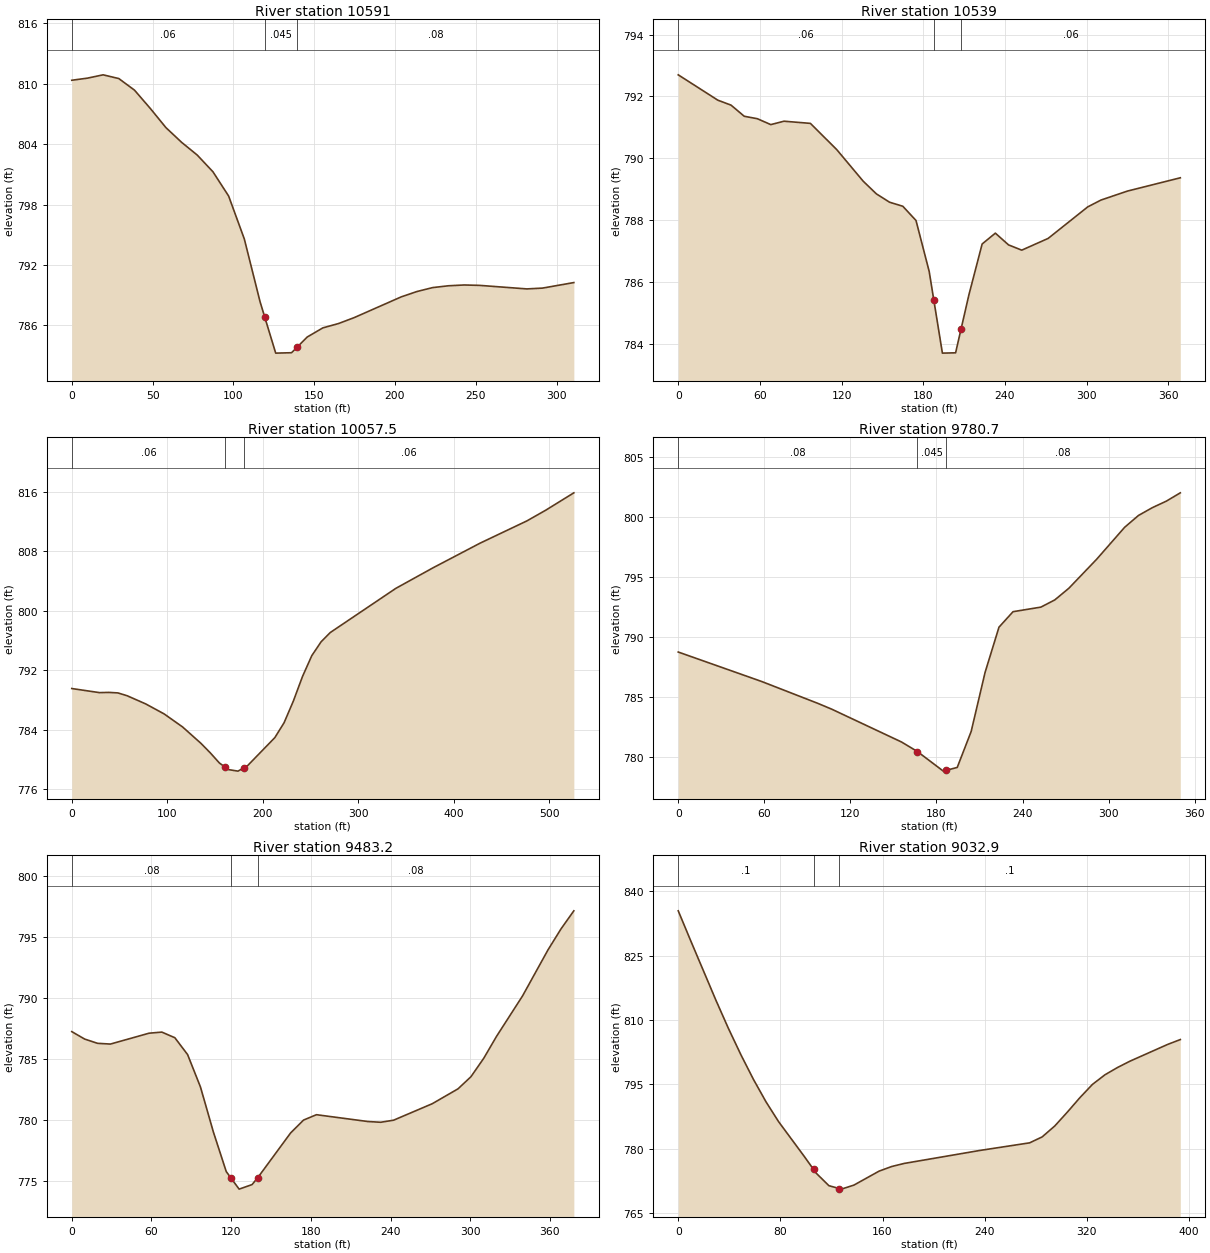
Type RM Length L Ch R = 1 ,10591   ,52.2,52,51.9
XS GIS Cut Line= 2
     1529329.629      259378.703     1529602.706      259230.432
#Sta/Elev= 30
       0  810.35     9.7  810.56    19.4  810.89    29.1  810.52    38.8  809.37
    48.6  807.55    58.3  805.64      68  804.18    77.7  802.91    87.4  801.25
    97.1  798.84   106.8  794.57   116.5  788.36   119.4786.8295   126.2  783.24
     136  783.28   139.4783.8234   145.7  784.84   155.4  785.75   165.1  786.18
   174.8  786.77   203.9  788.83   213.6  789.36   223.3  789.75     233  789.93
   242.8  790.01   252.5  789.97   281.6  789.62   291.3   789.7   310.7  790.25
#Mann= 3 , 0 , 0
       0     .06       0   119.4    .045       0   139.4     .08       0
Bank Sta=119.4,139.4
XS Rating Curve= 0 ,0
Exp/Cntr=0.3,0.1

Type RM Length L Ch R = 1 ,10539   ,446.4,481.5,515.9
XS GIS Cut Line= 2
     1529275.453      259460.452     1529601.838      259288.592
#Sta/Elev= 29
       0   792.7    29.1  791.88    38.8  791.72    48.5  791.36    58.2  791.28
      68  791.09    77.7   791.2    97.1  791.13   116.5  790.28   135.9  789.26
   145.6  788.85   155.3  788.58     165  788.45   174.7  787.99   184.4  786.34
   187.8785.4122   194.1   783.7   203.8  783.71   207.8784.4789   213.6  785.59
   223.3  787.23     233  787.58   242.7   787.2   252.4  787.03   271.8  787.41
   300.9  788.43   310.6  788.65     330  788.94   368.9  789.37
#Mann= 3 , 0 , 0
       0     .06       0   187.8    .045       0   207.8     .06       0
Bank Sta=187.8,207.8
XS Rating Curve= 0 ,0
Exp/Cntr=0.3,0.1

Type RM Length L Ch R = 1 ,10057.5 ,264.8,276.7,288.5
XS GIS Cut Line= 3
     1529210.079      259572.019     1529354.226      259801.075
     1529606.814      259836.208
#Sta/Elev= 29
       0  789.56      29  789.01    38.7  789.04    48.3  788.97      58  788.59
    77.3   787.5    96.7  786.15     116   784.4   135.3  782.19     145  780.92
   154.6  779.55   160.8778.9799   164.3  778.66     174  778.46   180.8778.9346
   183.6  779.13   212.6  782.96   222.3  784.96     232  787.87   241.6  791.18
   251.3  793.97     261  795.83   270.6  797.08   339.3  803.02   378.5   805.8
   427.6   809.1   476.6  812.09   496.2  813.52   525.7  815.86
#Mann= 3 , 0 , 0
       0     .06       0   160.8    .045       0   180.8     .06       0
Bank Sta=160.8,180.8
XS Rating Curve= 0 ,0
Exp/Cntr=0.3,0.1

Type RM Length L Ch R = 1 ,9780.7  ,297.8,297.6,297.5
XS GIS Cut Line= 2
     1529051.537      259633.796     1529064.545      259983.603
#Sta/Elev= 22
       0  788.73    58.3  786.27    97.2  784.46     107  783.97   155.6  781.24
   166.7780.4443   184.8  778.81   186.7778.8707   194.5  779.12   204.2  782.11
   213.9  787.03   223.6   790.8   233.4  792.09   252.8  792.47   262.5  793.07
   272.3  794.04   291.7  796.46   311.2  799.12   320.9  800.11   330.6  800.76
   340.3   801.3     350  801.99
#Mann= 3 , 0 , 0
       0     .08       0   166.7    .045       0   186.7     .08       0
Bank Sta=166.7,186.7
XS Rating Curve= 0 ,0
Exp/Cntr=0.3,0.1

Type RM Length L Ch R = 1 ,9483.2  ,461.7,450.2,437.9
XS GIS Cut Line= 2
     1528777.785      259614.716     1528791.834      259992.495
#Sta/Elev= 30
       0  787.25     9.7  786.64    19.4  786.29    29.1  786.23    58.2  787.12
    67.8  787.21    77.6  786.75    87.2  785.37    96.9  782.71   106.6  779.03
   116.3  775.78   120.1775.2131     126  774.34   135.7  774.71   140.1775.2902
   164.8  778.95   174.5     780   184.2  780.44     223  779.88   232.6  779.82
   242.3  779.99   271.4  781.34   290.8  782.56   300.5  783.55   310.2  785.07
   319.9  786.88   339.3  790.16   358.6  793.96   368.4  795.68     378  797.15
#Mann= 3 , 0 , 0
       0     .08       0   120.1    .045       0   140.1     .08       0
Bank Sta=120.1,140.1
XS Rating Curve= 0 ,0
Exp/Cntr=0.3,0.1

Type RM Length L Ch R = 1 ,9032.9  ,331.6,332.5,333.4
XS GIS Cut Line= 2
     1528298.693       259687.21     1528511.518      260017.793
#Sta/Elev= 30
       0  835.43     9.8  828.44    29.5  814.62    39.3  808.05    49.2  801.84
      59  796.12    68.8  790.92    78.6  786.33    98.3   778.4     106775.1943
   108.1  774.32     118  771.42     126770.7657   127.8  770.62   137.6  771.56
   157.3  774.81   167.1  775.88   176.9   776.6   235.9  779.61   275.2   781.4
     285  782.78   294.9  785.33   304.7  788.54   314.5   791.9   324.4  795.01
   334.2  797.25     344  798.94   353.8  800.42   383.3  804.32   393.2  805.45
#Mann= 3 , 0 , 0
       0      .1       0     106    .045       0     126      .1       0
Bank Sta=106,126
XS Rating Curve= 0 ,0
Exp/Cntr=0.3,0.1

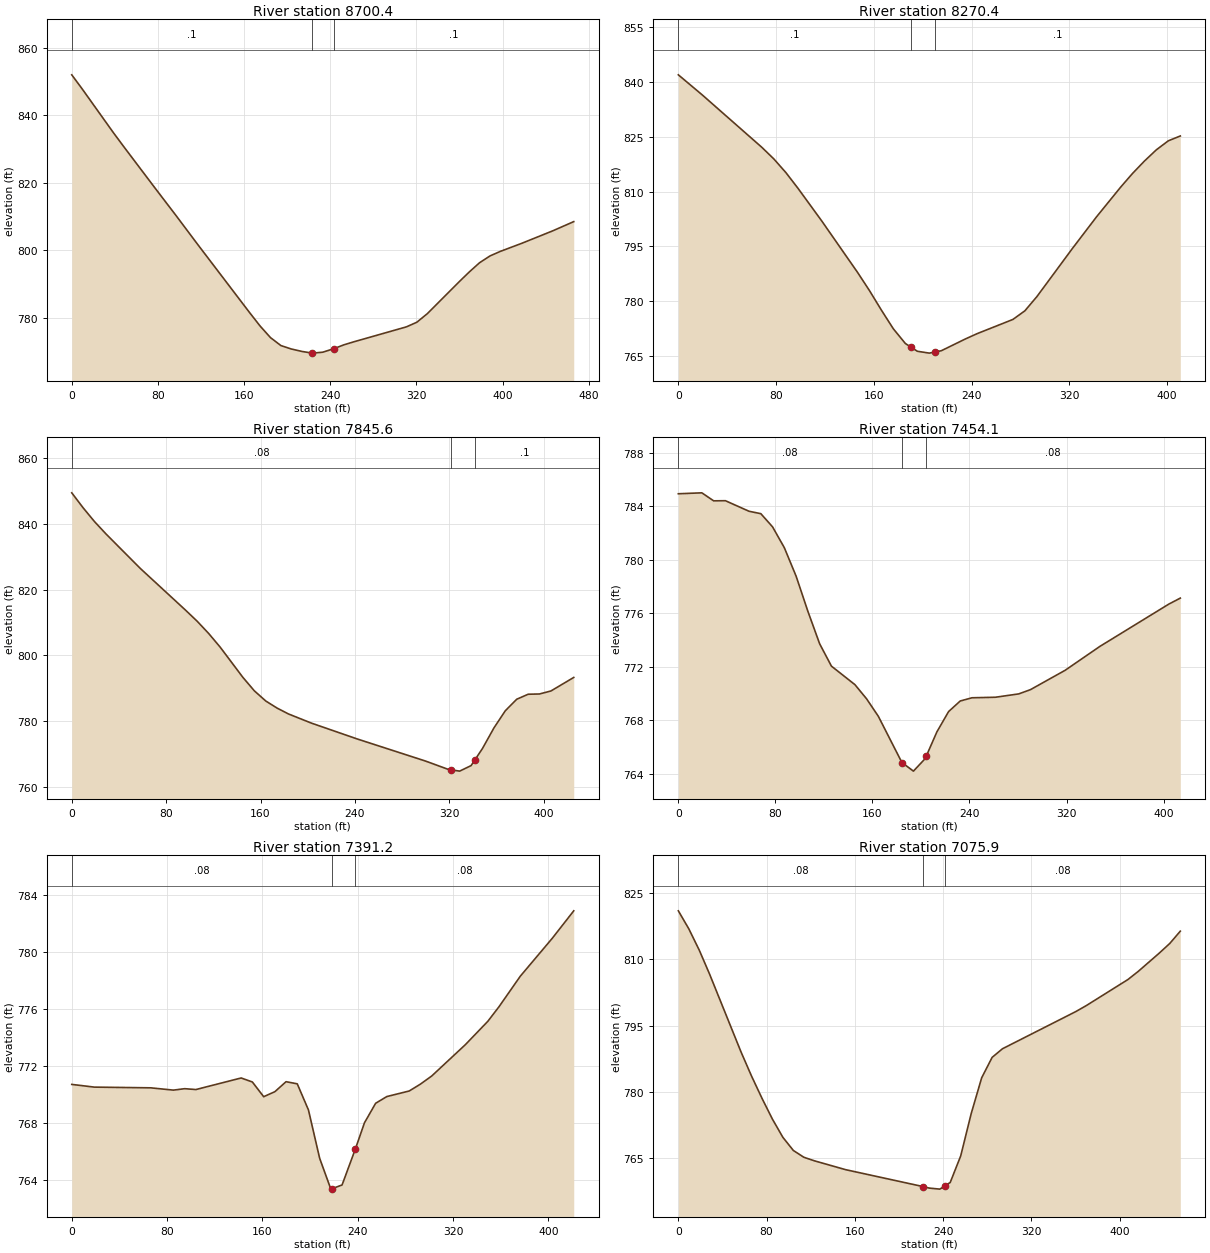
Type RM Length L Ch R = 1 ,8700.4  ,419,429.9,439.4
XS GIS Cut Line= 2
     1528006.962      259788.271     1528259.271      260180.186
#Sta/Elev= 30
       0     852     9.7  847.81    38.8  834.79    48.6  830.58    77.7  818.29
    97.1  810.18   116.5  801.92   165.1  781.55   174.8  777.59   184.5  774.13
   194.2  771.77   203.9  770.75   213.6  770.04   223.3  769.53   223.5769.5359
     233   769.8   243.5770.8659   252.5  771.97   262.2  772.91   310.7  777.31
   320.4  778.68   330.2  781.24   359.3  790.55     369  793.55   378.7  796.33
   388.4  798.34   398.1   799.7   417.6  802.04   446.7  805.78   466.1   808.5
#Mann= 3 , 0 , 0
       0      .1       0   223.5    .045       0   243.5      .1       0
Bank Sta=223.5,243.5
XS Rating Curve= 0 ,0
Exp/Cntr=0.3,0.1

Type RM Length L Ch R = 1 ,8270.4  ,404.9,424.8,444.8
XS GIS Cut Line= 2
     1527732.053      259856.332     1527779.796      260264.318
#Sta/Elev= 30
       0  841.93    19.6  836.43    68.5  822.06    78.2  818.92      88  815.21
    97.8  810.96   117.4  801.96   146.7   787.9   156.5   782.9   166.3  777.53
     176  772.47   185.8  768.47     190 767.561   195.6  766.35   205.4  765.84
     210766.1456   215.2  766.49   234.7  769.68   244.5  771.16   273.8  775.05
   283.6  777.41   293.4  781.28   322.8  794.59   342.3  803.13   361.9  811.19
   371.6  814.93   381.4  818.34   391.2  821.43     401  823.89   410.8  825.21
#Mann= 3 , 0 , 0
       0      .1       0     190    .045       0     210      .1       0
Bank Sta=190,210
XS Rating Curve= 0 ,0
Exp/Cntr=0.3,0.1

Type RM Length L Ch R = 1 ,7845.6  ,433.8,391.6,345.3
XS GIS Cut Line= 2
     1527597.114      259761.671     1527301.627      260067.746
#Sta/Elev= 30
       0  849.53     9.7  844.93    19.3  840.75      29     837      58  826.51
    96.7  813.67   106.4  810.34     116  806.66   125.7  802.52     145  793.28
   154.7  789.18   164.4  786.07     174  783.91   183.7  782.11     203  779.34
   241.7  774.52   299.7  767.77   319.1  765.22   321.7765.0773   328.7  764.69
   338.4  766.37   341.7768.1539   348.1  771.62   357.8  777.88   367.4  783.09
   377.1  786.61   386.8  788.13   396.4  788.21   406.1  789.13   425.4  793.25
#Mann= 3 , 0 , 0
       0     .08       0   321.7    .045       0   341.7      .1       0
Bank Sta=321.7,341.7
XS Rating Curve= 0 ,0
Exp/Cntr=0.3,0.1

Type RM Length L Ch R = 1 ,7454.1  ,62.8,62.9,62.9
XS GIS Cut Line= 4
     1526987.789      259786.924     1527037.932      259913.285
     1527189.067      259976.921     1527302.063      259991.045
#Sta/Elev= 30
       0  784.95    19.4  785.02    29.1  784.42    38.8  784.43    58.3  783.64
      68  783.46    77.7  782.47    87.4  780.91    97.1  778.78   106.8  776.15
   116.5  773.72   126.2  772.05   145.6  770.66   155.2   769.6   164.9  768.29
   184.3764.8331   193.8  764.19   203.5  765.13   204.3765.2958   213.1  767.12
   222.8  768.65   232.4  769.44   242.1  769.68   261.4  769.72   280.6  769.97
   290.3  770.29   318.9  771.74   347.4  773.52   404.3  776.69   413.8  777.14
#Mann= 3 , 0 , 0
       0     .08       0   184.3    .045       0   204.3     .08       0
Bank Sta=184.3,204.3
XS Rating Curve= 0 ,0
Exp/Cntr=0.3,0.1

Type RM Length L Ch R = 1 ,7391.2  ,287.2,315.3,343.1
XS GIS Cut Line= 4
      1526934.58      259811.755     1526994.009      259961.515
     1527175.973      260038.131     1527238.292      260045.921
#Sta/Elev= 30
       0  770.72      19  770.53    66.3  770.48    85.3  770.32    94.8  770.42
   104.2  770.36   142.2  771.17   151.6  770.89   161.1  769.86   170.5  770.21
   179.9  770.91   189.3  770.76   198.7  768.93   208.1  765.55   217.5  763.39
   218.1763.4094   226.9  763.68   238.1766.2028   245.7  768.03   255.1   769.4
   264.5  769.87   283.3  770.26   292.7  770.74   302.2  771.31   330.4   773.5
   349.2  775.13   358.6  776.15   376.5  778.29   403.4  780.95   421.4  782.87
#Mann= 3 , 0 , 0
       0     .08       0   218.1    .045       0   238.1     .08       0
Bank Sta=218.1,238.1
XS Rating Curve= 0 ,0
Exp/Cntr=0.3,0.1

Type RM Length L Ch R = 1 ,7075.9  ,452.4,432.6,411.5
XS GIS Cut Line= 3
     1526810.189      259898.162     1526803.837      260125.658
     1526791.881      260352.829
#Sta/Elev= 30
       0  820.97     9.5   816.9      19  812.06    28.4  806.61    56.9  789.01
    66.4  783.57    75.9  778.53    85.3  773.85    94.8  769.72   104.3  766.75
   113.8  765.22   123.3  764.42   151.7  762.41   221.6   758.6   227.6  758.24
   237.1  758.01   241.6758.7321   246.5  759.52     256  765.52   265.5  775.08
     275  783.19   284.5  787.82   293.9  789.77   360.3  798.17   369.8  799.52
   407.7  805.44   417.2  807.32   436.1  811.42   445.6   813.6   455.1  816.37
#Mann= 3 , 0 , 0
       0     .08       0   221.6    .045       0   241.6     .08       0
Bank Sta=221.6,241.6
XS Rating Curve= 0 ,0
Exp/Cntr=0.3,0.1

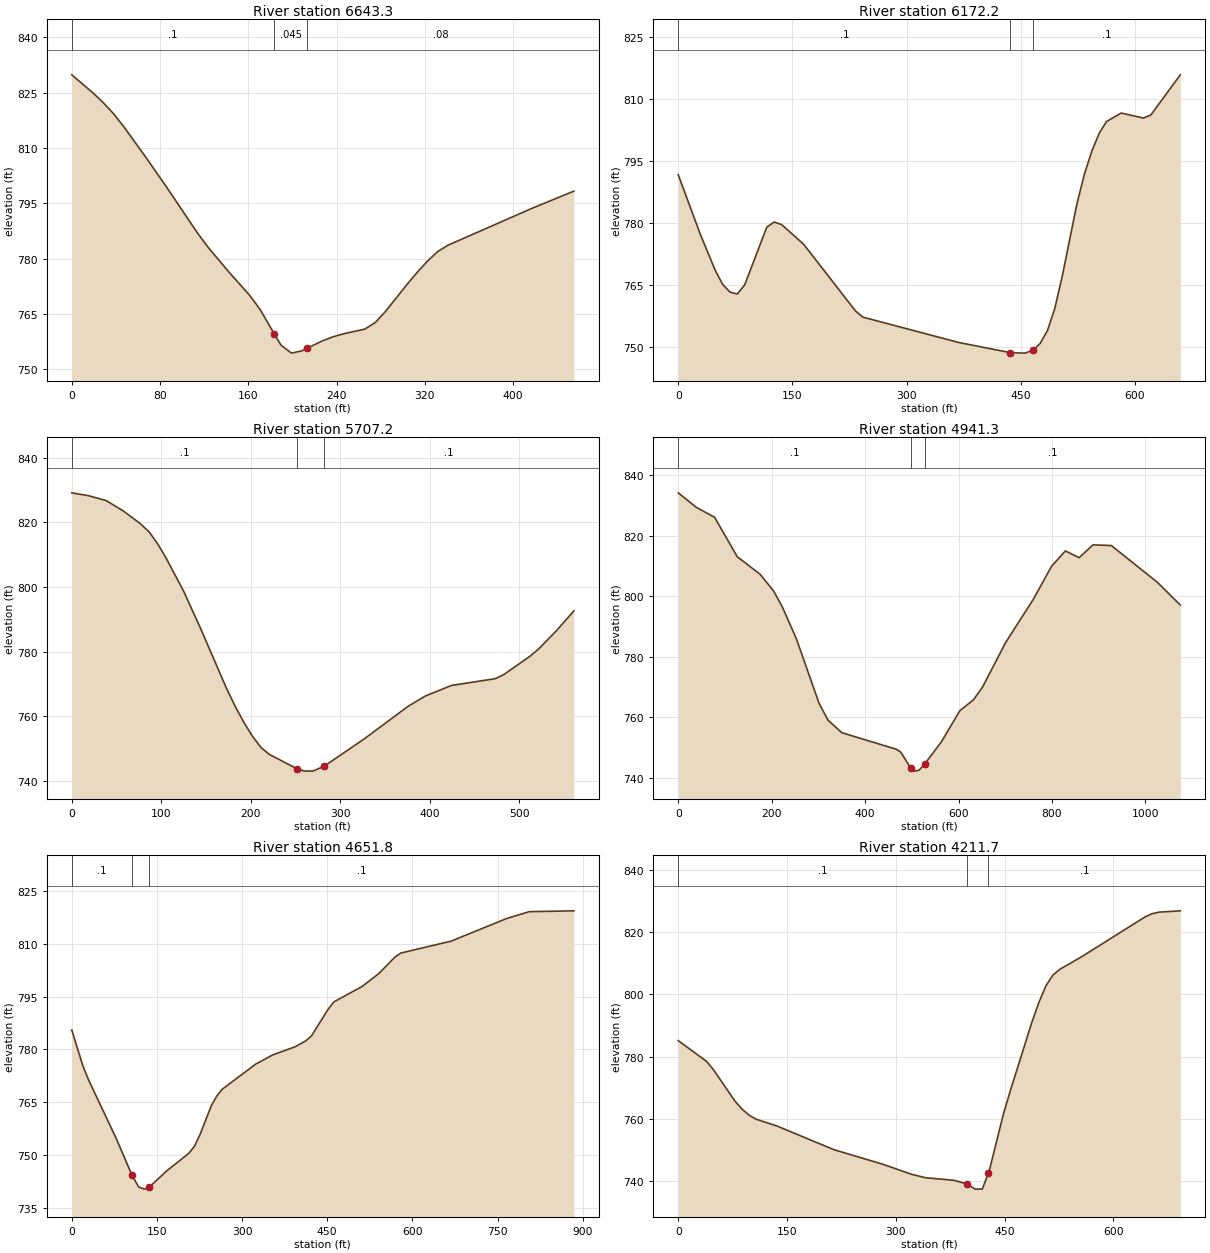
Type RM Length L Ch R = 1 ,6643.3  ,469.7,471.1,471.8
XS GIS Cut Line= 3
     1526253.556      260064.822     1526425.217      260214.245
     1526593.067      260367.789
#Sta/Elev= 30
       0  829.87      19  825.02    28.4  822.37    37.9  819.31    47.4   815.7
    66.4  807.81    85.3  799.69   113.8  787.02   123.3  783.18   142.2  776.44
   161.2  770.05   170.7  766.21   183.4759.6334   189.6  756.54   199.1  754.35
   208.6  754.97   213.4755.6976   227.6  757.73   237.1   758.8   246.5  759.61
   265.5  760.85     275  762.63   284.5  765.71   303.4  772.81   312.9   776.2
   322.4  779.32   331.8  781.94   341.3  783.67   417.2  793.65   455.1   798.3
#Mann= 3 , 0 , 0
       0      .1       0   183.4    .045       0   213.4     .08       0
Bank Sta=183.4,213.4
XS Rating Curve= 0 ,0
Exp/Cntr=0.3,0.1

Type RM Length L Ch R = 1 ,6172.2  ,453,465,476.4
XS GIS Cut Line= 2
     1525961.353       260246.34     1526422.527      260718.114
#Sta/Elev= 30
       0  791.66    29.1  777.22    48.5  768.58    58.2  765.18    67.9  763.29
    77.6   762.8    87.3  765.01   116.4     779   126.1  780.22   135.8  779.62
   164.9  774.83   232.8  758.73   242.6  757.21   368.7  751.07   436.3748.6149
     456   748.5   466.3749.2433   475.4  750.81   485.1  753.94   494.8  759.32
   504.5  767.05   523.9  784.66   533.6  791.75   543.3  797.32     553  801.66
   562.7  804.54   582.1   806.6   611.2  805.39   620.9  806.11   659.7  815.85
#Mann= 3 , 0 , 0
       0      .1       0   436.3    .045       0   466.3      .1       0
Bank Sta=436.3,466.3
XS Rating Curve= 0 ,0
Exp/Cntr=0.3,0.1

Type RM Length L Ch R = 1 ,5707.2  ,787.9,765.9,741.7
XS GIS Cut Line= 3
     1525779.799      260314.375     1525849.003      260623.854
     1525904.012      260861.116
#Sta/Elev= 30
       0  829.14    19.2  828.22    38.4  826.75    57.7  823.51    76.9  819.53
    86.5  817.02    96.1   813.3   105.7   808.8   124.9  798.76   144.2  787.01
     173  768.57   182.6  763.08   192.2  758.19   201.8  753.89   211.4  750.39
     221  748.23   251.7743.8103   259.5  743.15   269.1  743.11   281.7744.5944
   326.9  753.13   375.6  763.15   395.1  766.37   424.3  769.61     473  771.69
   482.7  772.99     512  778.68   521.7  780.96   541.2   786.5   560.7  792.64
#Mann= 3 , 0 , 0
       0      .1       0   251.7    .045       0   281.7      .1       0
Bank Sta=251.7,281.7
XS Rating Curve= 0 ,0
Exp/Cntr=0.3,0.1

Type RM Length L Ch R = 1 ,4941.3  ,280.4,289.5,296.3
XS GIS Cut Line= 4
     1525390.498      260786.162     1525581.703      261031.549
      1525885.29       261135.12     1526327.998      261140.329
#Sta/Elev= 30
       0   834.2    38.9  829.38    77.8  826.12   126.4  813.07     175  807.33
   204.2  801.75   223.6  796.24   252.8     786   301.4  764.66   320.8  759.04
     350  754.95   466.6  749.48   476.3  748.52     498743.1601   505.5  742.24
   515.2  742.52     528744.6852   563.8  752.06   602.7   762.2   631.8  765.79
   651.5  770.07   700.7  784.73   759.8  798.96   799.1  809.94   828.6  815.01
   858.1  812.77   887.7  817.01     927  816.78  1025.4  804.65  1074.6  797.13
#Mann= 3 , 0 , 0
       0      .1       0     498    .045       0     528      .1       0
Bank Sta=498,528
XS Rating Curve= 0 ,0
Exp/Cntr=0.3,0.1

Type RM Length L Ch R = 1 ,4651.8  ,412.7,440.1,468.8
XS GIS Cut Line= 2
     1525443.796       261094.66     1526042.868      261745.275
#Sta/Elev= 30
       0  785.52    19.6  775.34    29.5   771.4    78.6  754.65   106.2744.2883
   117.9     741   127.8  740.39   136.2740.9135   167.1  745.54   206.4  750.57
   216.2  752.56     226  755.89   245.7     764   255.5   766.8   265.3  768.74
   324.3  775.87   353.8  778.44   393.1  780.73   412.7  782.47   422.6  783.92
     452   791.5   461.9   793.5     511  797.81   540.5  801.46     570  806.29
   579.8  807.34   668.2   810.7   766.5  817.15   805.8  819.06   884.4   819.3
#Mann= 3 , 0 , 0
       0      .1       0   106.2    .045       0   136.2      .1       0
Bank Sta=106.2,136.2
XS Rating Curve= 0 ,0
Exp/Cntr=0.3,0.1

Type RM Length L Ch R = 1 ,4211.7  ,402.7,411.4,415.1
XS GIS Cut Line= 2
     1525405.901       261117.25     1525184.769      261773.141
#Sta/Elev= 30
       0   785.1      39  778.45    48.7  775.73      78  765.75    87.7  763.15
    97.5  761.21   107.2  759.88   136.5  757.65   214.5  750.09   282.7  745.35
   321.7  742.17   341.2  741.06   380.2  740.24   397.6739.1191   409.4  737.41
   419.2  737.43   427.6742.6064     429  743.47   448.4   761.6   458.2  769.27
   487.4  790.89   497.2  797.32   506.9  802.69   516.7  806.18   526.4  808.04
   555.7  811.97   643.4   824.8   653.2  825.85   662.9  826.36   692.2  826.78
#Mann= 3 , 0 , 0
       0      .1       0   397.6    .045       0   427.6      .1       0
Bank Sta=397.6,427.6
XS Rating Curve= 0 ,0
Exp/Cntr=0.3,0.1

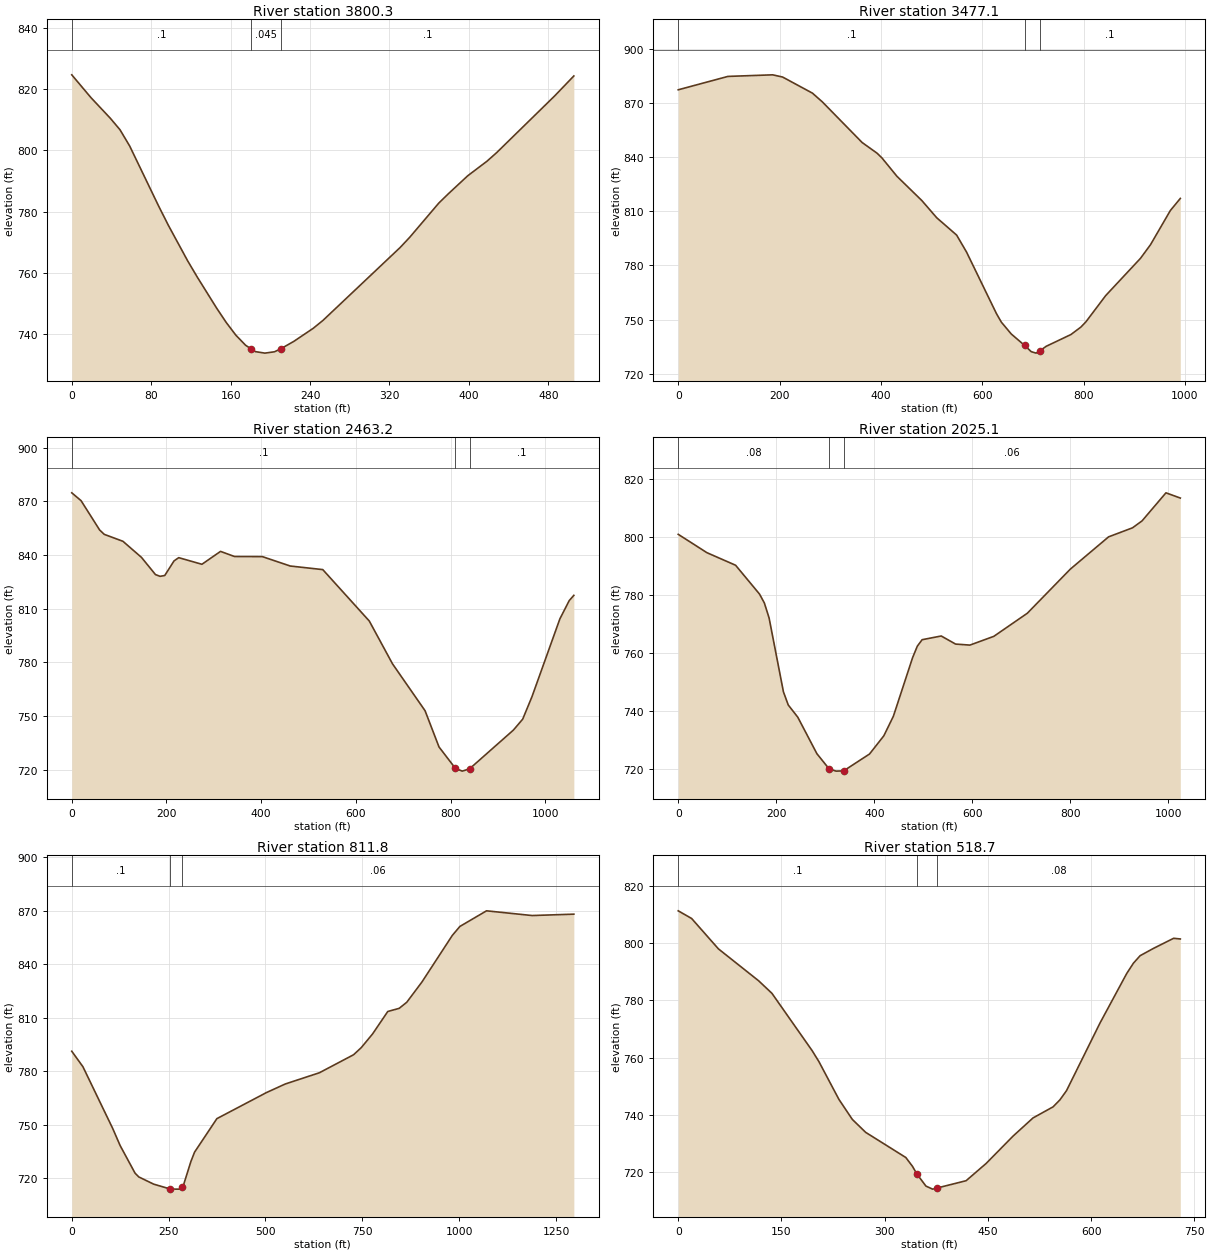
Type RM Length L Ch R = 1 ,3800.3  ,327.9,323.2,321.2
XS GIS Cut Line= 2
     1525329.969      260998.239     1524999.127      261380.756
#Sta/Elev= 30
       0  824.72    19.4  817.24    38.9   810.5    48.6  806.76    58.4  801.41
    87.5  781.82    97.3  775.53   116.7  763.94   126.4  758.62   145.9  748.48
   155.6  743.77   165.3  739.62   175.1  736.33   180.6735.1563   184.8  734.26
   194.5  733.76   204.2   734.2   210.6735.1862   223.7  737.61   243.2  741.87
   252.9  744.42   330.7  768.27   340.4  771.62   369.6  782.77   379.3  785.84
   398.8  791.72   418.2  796.48   427.9  799.27   486.3   817.8   505.7  824.35
#Mann= 3 , 0 , 0
       0      .1       0   180.6    .045       0   210.6      .1       0
Bank Sta=180.6,210.6
XS Rating Curve= 0 ,0
Exp/Cntr=0.3,0.1

Type RM Length L Ch R = 1 ,3477.1  ,1040.5,1013.9,983
XS GIS Cut Line= 2
     1525257.401      260321.867     1524824.289      261213.239
#Sta/Elev= 30
       0  877.37    98.1  884.79   186.4  885.67     206  884.44   264.9  875.52
   284.6  870.63     363  848.14   392.5  842.22   402.3  839.53   431.7  829.42
   480.8  815.98   510.2  806.44   549.5  796.83   569.1   787.4     628  753.34
   637.8  748.55   657.4  741.98   683.8735.6276   696.7  732.21   706.3  731.39
   713.8  732.65   726.1  735.15   775.2  741.71   794.8  745.84   804.6  748.71
   843.8  763.31   912.5  783.97   932.2  791.51   971.4  810.47     991  817.14
#Mann= 3 , 0 , 0
       0      .1       0   683.8    .045       0   713.8      .1       0
Bank Sta=683.8,713.8
XS Rating Curve= 0 ,0
Exp/Cntr=0.3,0.1

Type RM Length L Ch R = 1 ,2463.2  ,449.4,438.1,429.4
XS GIS Cut Line= 2
     1523950.827      260584.698     1524775.589        261250.7
#Sta/Elev= 30
       0  874.71    19.6  870.34    58.9  853.92    68.7  851.48     108  847.62
   147.2  838.62   176.7  829.01   186.5  828.02   196.3  828.49   215.9  836.64
   225.8  838.47   274.8  834.76   314.1  841.97   343.6  839.11   402.4  839.05
   461.3  833.79     530  831.79   628.2  803.04   677.3  779.08     746  752.88
   775.4  732.64   809.9720.7153   824.5  719.13   839.9720.4128   932.5  742.08
   952.1  748.18   971.8  760.81  1030.6  804.23  1050.3  814.44  1060.1   817.4
#Mann= 3 , 0 , 0
       0      .1       0   809.9    .045       0   839.9      .1       0
Bank Sta=809.9,839.9
XS Rating Curve= 0 ,0
Exp/Cntr=0.3,0.1

Type RM Length L Ch R = 1 ,2025.1  ,1184.9,1213.2,1240.9
XS GIS Cut Line= 2
     1524018.108      261272.882     1524952.288      261692.752
#Sta/Elev= 30
       0  800.77    58.5  794.44     117  790.11   165.8  780.17   175.6  777.13
   185.3  771.96   214.6  746.45   224.4  741.93   243.9   737.7   282.9  725.11
   307.4719.9663   321.9  719.11   337.4719.1988   390.2  725.01   419.4  731.29
   438.9  738.04     478   758.2   487.7  762.19   497.5  764.43   536.5  765.71
   565.8  762.92     595  762.57   643.8  765.59   712.1  773.55   799.8  788.76
   877.9   799.9   926.7  803.01   946.2  805.41   994.9  815.08  1024.2  813.28
#Mann= 3 , 0 , 0
       0     .08       0   307.4    .045       0   337.4     .06       0
Bank Sta=307.4,337.4
XS Rating Curve= 0 ,0
Exp/Cntr=0.3,0.1

Type RM Length L Ch R = 1 ,811.8   ,312.6,293.1,271.1
XS GIS Cut Line= 3
     1523921.743      261549.324     1523912.714      261923.819
     1524654.392      262470.531
#Sta/Elev= 30
       0  791.23    28.8  782.56   105.7  747.96   124.9  738.38   163.3  722.97
   172.9  720.84   211.3   716.8   254.1 714.075     269     714   278.6     714
   284.1715.2261   288.2  716.14   307.4  729.41     317  734.72   374.6  753.48
     502  768.02     551  772.88   639.3  779.19   727.5  789.28   747.1  793.22
   776.5  800.93   815.7   813.5   845.1  815.25   864.7  818.66   903.9  830.02
   982.3  856.11  1001.9  861.14  1070.6  869.88  1188.2  867.24    1296  868.01
#Mann= 3 , 0 , 0
       0      .1       0   254.1    .045       0   284.1     .06       0
Bank Sta=254.1,284.1
XS Rating Curve= 0 ,0
Exp/Cntr=0.3,0.1

Type RM Length L Ch R = 1 ,518.7   ,89.9,82,79
XS GIS Cut Line= 2
     1523362.141      261574.369     1523938.682      262021.629
#Sta/Elev= 30
       0   811.2    19.5  808.52    58.4  797.92   116.8  786.79   136.2   782.4
   194.6   762.4   204.3  758.64   233.5   745.4     253   738.4   272.4  733.88
   330.8  725.09   340.5     722   346.7719.3857     360  715.12   369.7  714.06
   376.7714.4786   418.4     717   447.5  723.02   486.5  732.54   515.6   738.9
   544.8  742.78   554.6  745.18   564.3  748.42   612.9     772   651.8  789.32
   661.6  792.94   671.3  795.54   690.8   798.1     720  801.61   729.7  801.38
#Mann= 3 , 0 , 0
       0      .1       0   346.7    .045       0   376.7     .08       0
Bank Sta=346.7,376.7
XS Rating Curve= 0 ,0
Exp/Cntr=0.3,0.1

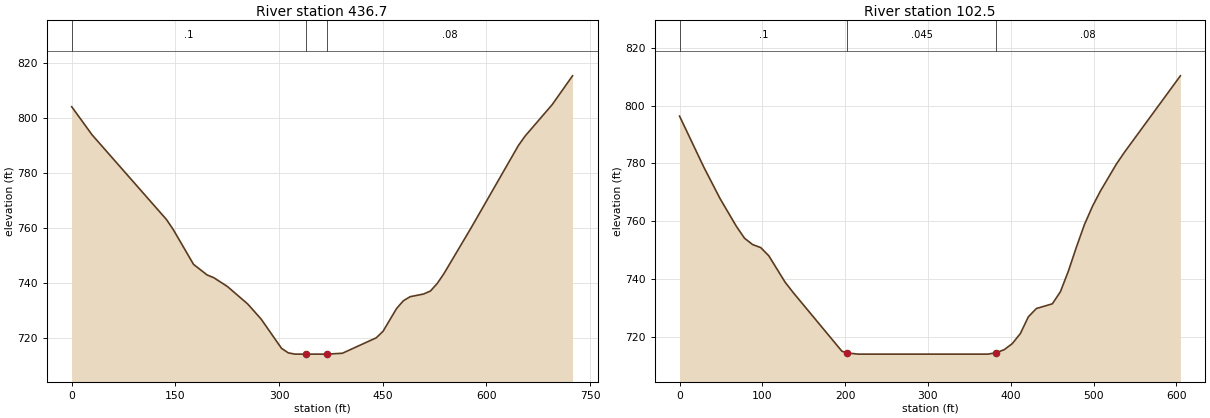
Type RM Length L Ch R = 1 ,436.7   ,306.7,334.2,357.4
XS GIS Cut Line= 2
     1523289.234      261617.107     1523870.286      262050.167
#Sta/Elev= 30
       0  804.05    29.4  793.84   137.1     763   146.9  759.36   176.3  746.67
   195.9  742.82   205.6  741.82   225.2  738.64   254.6  732.27   274.2  726.73
   303.6  716.11   313.4  714.46   323.2     714   339.7714.0032   369.7     714
   391.7  714.32   440.7  719.94   450.5  722.32   470.1  730.59   479.9  733.42
   489.6  734.89   509.2  735.88     519  736.95   528.8  739.67   538.6  743.28
   577.8  759.89   646.3   789.9   656.1  793.36   695.3  804.82   724.7  815.29
#Mann= 3 , 0 , 0
       0      .1       0   339.7    .045       0   369.7     .08       0
Bank Sta=339.7,369.7
XS Rating Curve= 0 ,0
Exp/Cntr=0.3,0.1

Type RM Length L Ch R = 1 ,102.5   ,111.8,102.5,93.2
XS GIS Cut Line= 3
     1523219.832      261647.532     1523277.478       262055.06
     1523422.856       262182.31
#Sta/Elev= 30
       0  796.35    29.4  778.64      49  767.77    68.6  758.23    78.4  754.12
    88.2  751.91      98  750.87   107.8  748.02   127.4  738.92   137.2  735.32
     196  715.03   202.2714.4227   215.6     714   372.4     714   382.2  714.48
     392  715.53   401.8  717.64   411.6  721.13   421.2   726.9   430.9  729.78
   450.2  731.41   459.9  735.57   469.6  742.76   479.2  750.99   488.9  758.79
   498.5  765.05   508.2   770.4   527.5  779.74   537.2  783.82   604.8  810.29
#Mann= 3 , 0 , 0
       0      .1       0   202.2    .045       0   382.2     .08       0
Bank Sta=202.2,382.2
XS Rating Curve= 0 ,0
Exp/Cntr=0.3,0.1

Chan Stop Cuts=-1
Use User Specified Reach Order=0
Composite Channel Slope=5